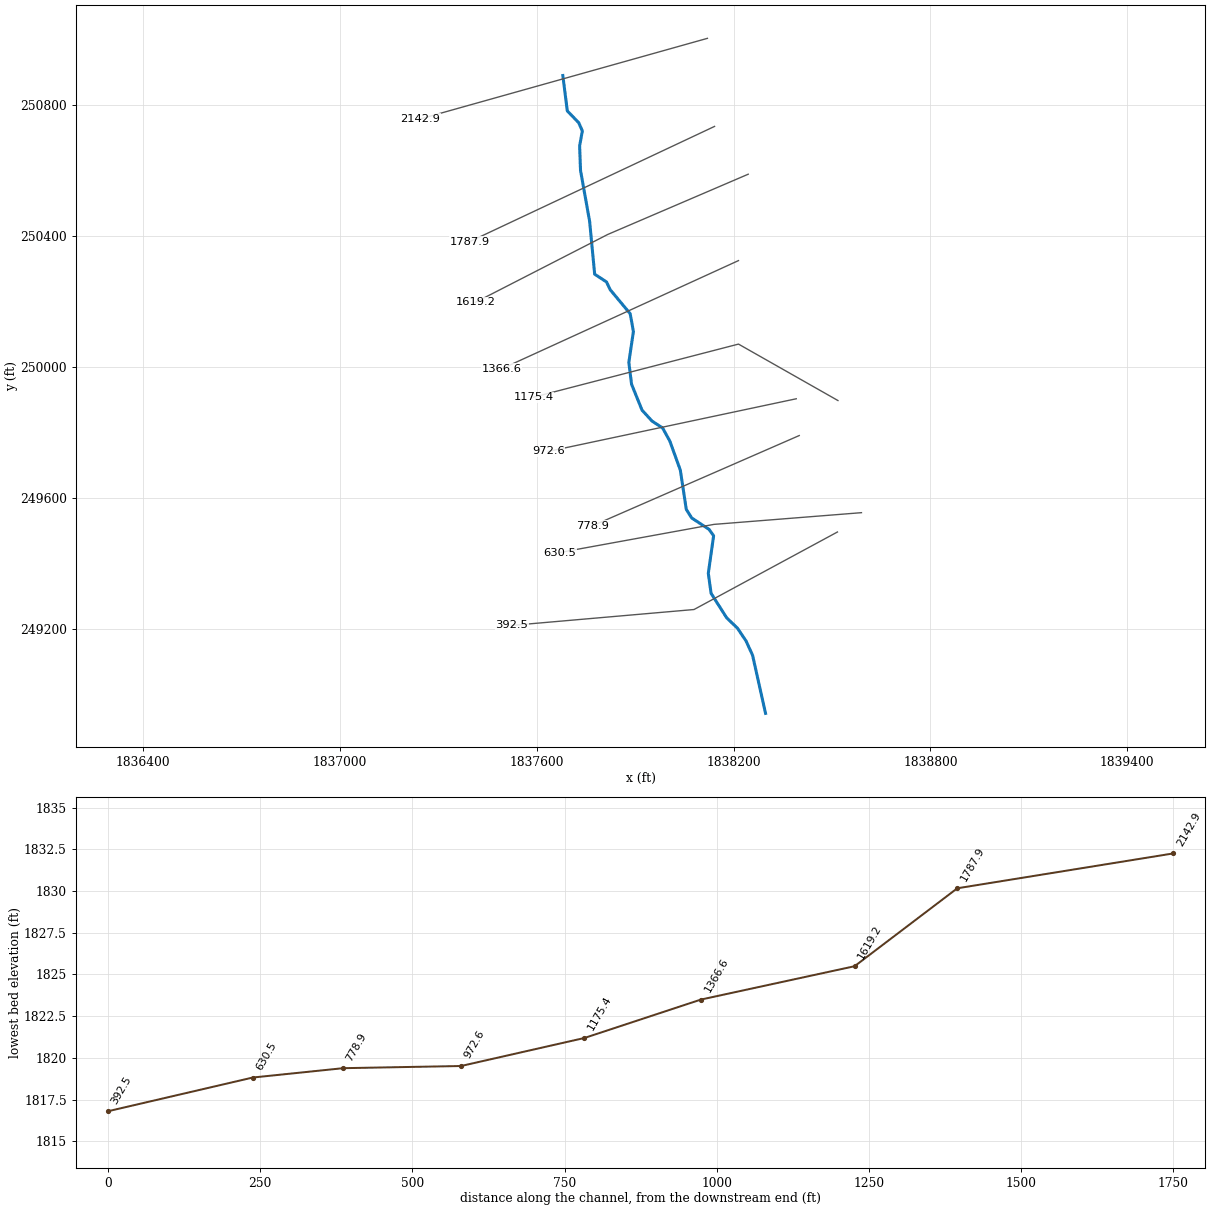
--- NP1537.prj (project) ---

Proj Title=NP1537
Current Plan=p01
Default Exp/Contr=0,0
English Units
Geom File=g01
Flow File=f01
Plan File=p01
BEGIN DESCRIPTION:
END DESCRIPTION:
DSS Export Rating Curves= 0
DSS Export Rating Curve Sorted= 0
DSS Export Volume Flow Curves= 0
DXF OffsetX= 0
DXF OffsetY= 0
DXF ScaleX= 0
DXF ScaleY= 0

--- NP1537.p01 (plan) ---

Plan Title=Floodplain
Program Version=4.00
Geom File=g01
Flow File=f01
K Sum by GR=0
Std Step Tol=0.01
Critical Tol=0.01
Num of Std Step Trials=20
Max Error Tol=0.3
Flow Tol Ratio=0.001
Split Flow NTrial=30
Split Flow Tol=0.02
Split Flow Ratio=0.02
Log Output Level=0
Friction Slope Method=1
Unsteady Friction Slope Method=2
Unsteady Bridges Friction Slope Method=1
Global Log Level=0
CheckData=False
Run HTab=0
Run UNet=0
Run PostProcess=0
UNET Theta=0
UNET Theta Warmup=0
UNET ZTol=0
UNET ZSATol=0
UNET MxIter=0
UNET MaxInSteps=0
UNET DtIC=0
UNET DtMin=0
UNET MaxCRTS=0
UNET WFStab=0
UNET SFStab=0
UNET WFX=0
UNET SFX=0
UNET DSS MLevel=0
UNET DZMax Abort=0
UNET Convert EG Bridges=0
UNET Use Existing IB Tables=0
UNET Froude Limit=0
UNET Froude Power=0
Write IC File=0
Echo Input=False
Echo Output=False
Write Detailed=0

--- NP1537.f01 (steady flow) ---

Flow Title=NFF Regression Equation
Program Version=4.00
Number of Profiles=1
Profile Names=P100yr
River Rch & RM=NP1537,Main      ,2142.9
538.0474
River Rch & RM=NP1537,Main      ,1366.6
543.6870
River Rch & RM=NP1537,Main      ,1175.4
635.0201
Boundary for River Rch & Prof#=NP1537,Main      ,1
Up Type=0
Dn Type=3
Dn Slope=0.002756

--- NP1537.g01 (geometry) ---

Geom Title=USGS 10m DEM
Program Version=4.00

River Reach=NP1537          ,Main
Reach XY= 30
     1837679.627      250889.021     1837693.289      250780.967
     1837728.019      250744.848     1837739.132      250719.843
     1837730.797      250673.999     1837733.576      250598.981
      1837761.36      250443.391     1837776.641      250282.243
      1837812.76      250258.626     1837823.874      250235.009
     1837884.999      250161.382     1837894.723      250107.203
     1837880.831      250012.737     1837889.167      249946.055
     1837921.118       249866.87     1837951.681      249833.529
     1837983.633      249812.691      1838005.86      249772.404
     1838037.812      249683.495     1838055.871      249564.023
     1838072.542      249537.628     1838125.332      249502.898
     1838139.224      249483.449     1838123.027      249368.791
     1838131.473       249307.56     1838179.176      249232.484
     1838211.753      249201.349     1838237.933      249162.317
     1838257.925      249118.525     1838297.484      248940.949

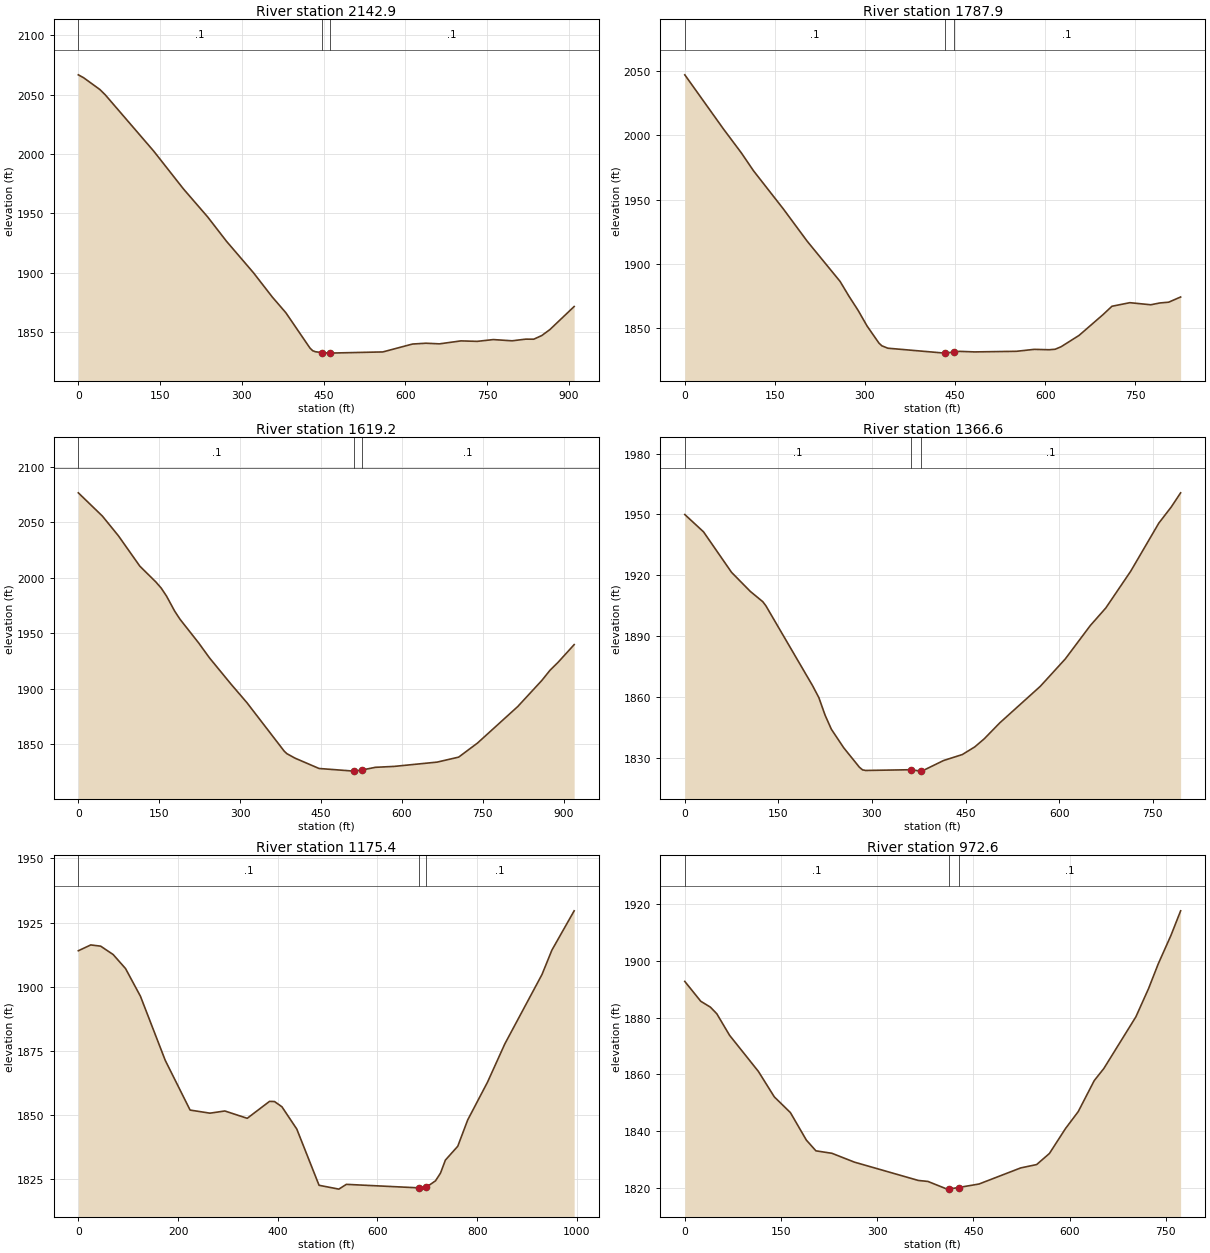
Type RM Length L Ch R = 1 ,2142.9  ,350.9,355.1,359.2
XS GIS Cut Line= 3
      1838120.34      251002.585     1837682.334      250879.394
     1837244.329      250756.204
#Sta/Elev= 30
       0 2066.67     9.9 2064.16    39.6 2054.27    49.5 2049.79   138.5 2002.33
   192.9 1970.57   237.4 1946.95     272 1926.42   321.5 1899.92   356.1 1879.44
   380.8 1866.32   425.3  1836.4   430.3 1834.25   435.2 1833.42   447.5 1832.71
     460 1832.25   462.5 1832.29   558.9 1833.26   613.3  1839.9     638 1840.59
   662.7 1840.06   702.3 1842.56     732 1842.16   761.6 1843.66   796.2 1842.63
     821 1844.03   835.8 1843.98   850.6 1847.06   865.5  1852.1     910 1871.51
#Mann= 3 , 0 , 0
       0      .1       0   447.5    .045       0   462.5      .1       0
Bank Sta=447.5,462.5
XS Rating Curve= 0 ,0
Exp/Cntr=0.3,0.1

Type RM Length L Ch R = 1 ,1787.9  ,167.9,168.7,169.5
XS GIS Cut Line= 2
     1838142.104      250733.631      1837395.27      250381.465
#Sta/Elev= 30
       0 2047.29    64.7 2004.83    94.5 1986.17   114.4 1972.44   164.2  1942.6
   203.9 1917.43   258.6 1886.11   273.6 1874.41   288.5 1863.62   303.4 1851.42
   323.3 1837.99   328.3 1835.84   338.2    1834   432.8 1830.16   447.8 1831.02
   457.6 1831.54   482.5 1831.11   552.1 1831.58     582  1833.1   606.8  1832.8
   616.8 1833.19   626.7 1835.15   656.6    1844   696.4 1860.17   711.3 1866.72
   741.1 1869.51     776 1867.89   790.9 1869.28   805.8 1869.91   825.7 1873.95
#Mann= 3 , 0 , 0
       0      .1       0   432.8    .045       0   447.8      .1       0
Bank Sta=432.8,447.8
XS Rating Curve= 0 ,0
Exp/Cntr=0.3,0.1

Type RM Length L Ch R = 1 ,1619.2  ,253.7,252.6,251.5
XS GIS Cut Line= 3
      1838244.69       250587.62     1837816.517      250403.594
      1837413.56      250196.518
#Sta/Elev= 30
       0 2076.79    44.6 2055.79    74.4 2037.93     114 2010.58   143.8 1996.26
   153.7 1990.71   163.6 1983.46   178.5 1970.04   188.4 1962.68   223.1 1941.22
   242.9 1927.89   282.6  1904.3   312.4 1887.38   381.8 1843.43   386.7 1841.21
   401.6 1837.23   446.2 1827.88   510.8 1825.49   511.4 1825.51   526.4 1826.57
   550.7 1828.93   585.5 1829.76   665.2 1833.64     705 1838.14   739.9 1850.82
   814.6 1883.84   859.4  1907.5   874.3 1916.54   889.2  1923.7   919.1 1939.71
#Mann= 3 , 0 , 0
       0      .1       0   511.4    .045       0   526.4      .1       0
Bank Sta=511.4,526.4
XS Rating Curve= 0 ,0
Exp/Cntr=0.3,0.1

Type RM Length L Ch R = 1 ,1366.6  ,195.2,191.2,187.2
XS GIS Cut Line= 2
     1838214.966      250323.783     1837492.419      249992.868
#Sta/Elev= 30
       0 1949.94      30 1941.42      75 1921.43     105 1912.06     125 1906.99
     130 1904.96   204.9 1865.55   214.9  1859.7   224.9 1851.03   234.9 1844.14
   254.9 1834.92   279.9  1825.4   284.9 1824.11   289.9 1823.82   362.8 1824.18
   377.8  1823.5   379.9 1823.49   414.8 1828.72   444.8 1831.66   464.8 1835.44
   479.8 1839.37   504.8 1847.26   569.8 1865.29   609.8 1878.76   649.8 1895.18
   674.8  1903.9   714.8 1922.06   759.7 1945.69   779.7 1953.67   794.7 1960.64
#Mann= 3 , 0 , 0
       0      .1       0   362.8    .045       0   377.8      .1       0
Bank Sta=362.8,377.8
XS Rating Curve= 0 ,0
Exp/Cntr=0.3,0.1

Type RM Length L Ch R = 1 ,1175.4  ,205,202.8,197.2
XS GIS Cut Line= 3
     1838518.127      249896.386     1838214.966      250068.766
     1837589.786      249906.436
#Sta/Elev= 30
       0 1914.02    24.9 1916.29    44.8 1915.81    69.8 1912.56    94.7 1907.09
   124.6  1896.3   174.4 1871.32   224.2 1851.98     264 1850.77   293.9 1851.62
   338.8 1848.77   383.5 1855.36   393.5  1855.3   408.4 1853.26   438.2 1844.59
   482.9 1822.68   522.6 1821.19   537.6 1823.05   682.5 1821.69   697.5 1821.88
   716.4 1824.41   726.4  1827.4   736.3 1832.49   761.1 1837.88     781 1848.11
   820.8 1862.85   855.5 1877.74   930.1 1904.78   949.9 1914.25   994.6 1929.57
#Mann= 3 , 0 , 0
       0      .1       0   682.5    .045       0   697.5      .1       0
Bank Sta=682.5,697.5
XS Rating Curve= 0 ,0
Exp/Cntr=0.3,0.1

Type RM Length L Ch R = 1 ,972.6   ,187.9,193.6,202.9
XS GIS Cut Line= 2
     1838391.049      249901.791     1837635.107      249740.888
#Sta/Elev= 30
       0 1892.79    24.9 1885.79    39.9 1883.72    49.9 1881.38    69.8 1873.78
   114.7 1861.05   139.6 1852.04   164.6 1846.52   189.5 1836.81   204.4 1833.02
   229.4 1832.15   264.3 1829.04     364 1822.57     379 1822.22   408.9 1819.51
   411.9 1819.56   426.9 1820.08   458.7 1821.32   523.6 1826.99   548.5 1828.18
   568.4 1832.09   593.4 1840.87   613.3 1846.86   638.2 1857.78   653.2 1862.07
   703.1 1880.28     723 1890.31     738 1898.98   757.9 1909.07   772.9  1917.7
#Mann= 3 , 0 , 0
       0      .1       0   411.9    .045       0   426.9      .1       0
Bank Sta=411.9,426.9
XS Rating Curve= 0 ,0
Exp/Cntr=0.3,0.1

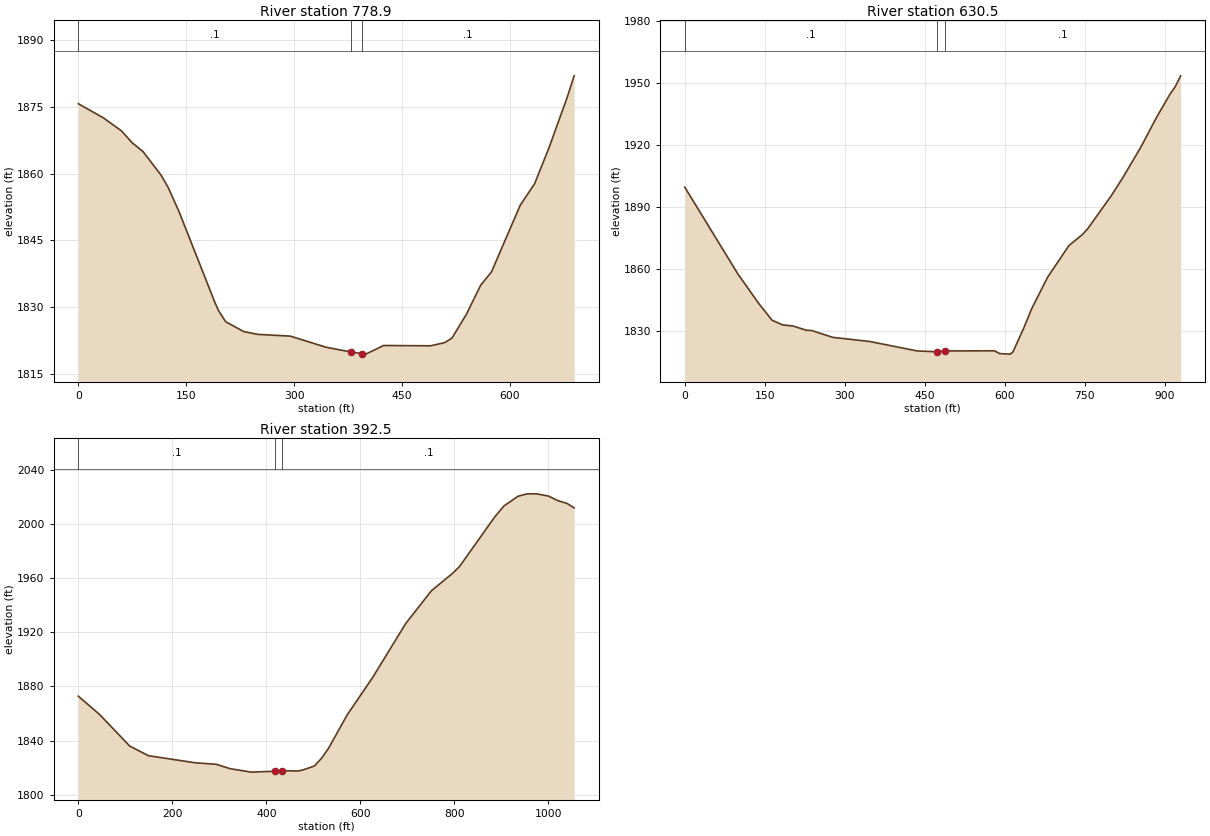
Type RM Length L Ch R = 1 ,778.9   ,157.9,148.4,137.9
XS GIS Cut Line= 2
     1838400.157      249789.462     1837768.687      249513.194
#Sta/Elev= 30
       0  1875.7      35  1872.5    59.9  1869.6    74.9 1866.91    89.9 1864.94
   114.9 1859.67   124.9 1856.86   139.8  1851.5   189.8 1831.03   194.8 1829.21
   204.8 1826.67   229.8 1824.46   249.7 1823.82   294.7 1823.43   344.6 1820.92
   379.2 1819.86   394.2 1819.48   399.6 1819.38   424.5 1821.32   489.5 1821.25
   509.4 1821.97   519.4 1822.98   539.4 1828.31   559.4 1834.89   574.4 1837.88
   614.3 1852.86   634.3  1857.7   654.3 1865.77   679.3 1876.98   689.3 1881.97
#Mann= 3 , 0 , 0
       0      .1       0   379.2    .045       0   394.2      .1       0
Bank Sta=379.2,394.2
XS Rating Curve= 0 ,0
Exp/Cntr=0.3,0.1

Type RM Length L Ch R = 1 ,630.5   ,226.5,237.9,249.9
XS GIS Cut Line= 3
     1838589.784      249553.918     1838140.375      249518.168
     1837669.536      249432.121
#Sta/Elev= 30
       0 1899.67    99.1 1857.83   138.7 1843.33   163.5 1835.27   183.3 1832.98
   203.1 1832.43   227.9 1830.38   237.8 1830.26   277.4 1826.94   346.8 1824.93
     436 1820.35   472.8 1819.95   487.8 1820.36   580.5 1820.43   590.4 1819.07
   610.4 1818.82   615.4 1820.02   635.3 1831.38   650.3  1840.8   680.2  1856.1
   720.1  1871.4     745 1876.66     755 1879.43   799.8 1895.66   819.8 1903.72
   854.7 1918.97   884.6  1933.6   909.5 1944.71   919.5 1948.42   929.5 1953.62
#Mann= 3 , 0 , 0
       0      .1       0   472.8    .045       0   487.8      .1       0
Bank Sta=472.8,487.8
XS Rating Curve= 0 ,0
Exp/Cntr=0.3,0.1

Type RM Length L Ch R = 1 ,392.5   ,400.3,392.5,384.7
XS GIS Cut Line= 3
     1838516.626      249494.939     1838079.455      249258.138
     1837523.883      249209.564
#Sta/Elev= 30
       0 1872.84    44.8 1859.48   109.4 1836.02   149.2 1828.92   248.6  1823.7
   293.3 1822.59   323.2 1819.32   367.9  1816.8   419.1 1817.45   434.1 1817.85
   467.4 1817.63   477.3 1818.34   502.2 1821.32   517.1 1826.87     532 1834.19
   571.9 1858.96   626.6 1886.85   696.4 1926.37   751.1  1950.6     796 1963.41
   810.9 1968.44   885.6 2004.96   905.5  2013.2   935.4 2020.36   955.3 2022.15
   975.2 2022.13  1000.1 2020.51    1020 2017.15  1039.9 2015.03  1054.9 2011.76
#Mann= 3 , 0 , 0
       0      .1       0   419.1    .045       0   434.1      .1       0
Bank Sta=419.1,434.1
XS Rating Curve= 0 ,0
Exp/Cntr=0.3,0.1

Chan Stop Cuts=-1
Use User Specified Reach Order=0